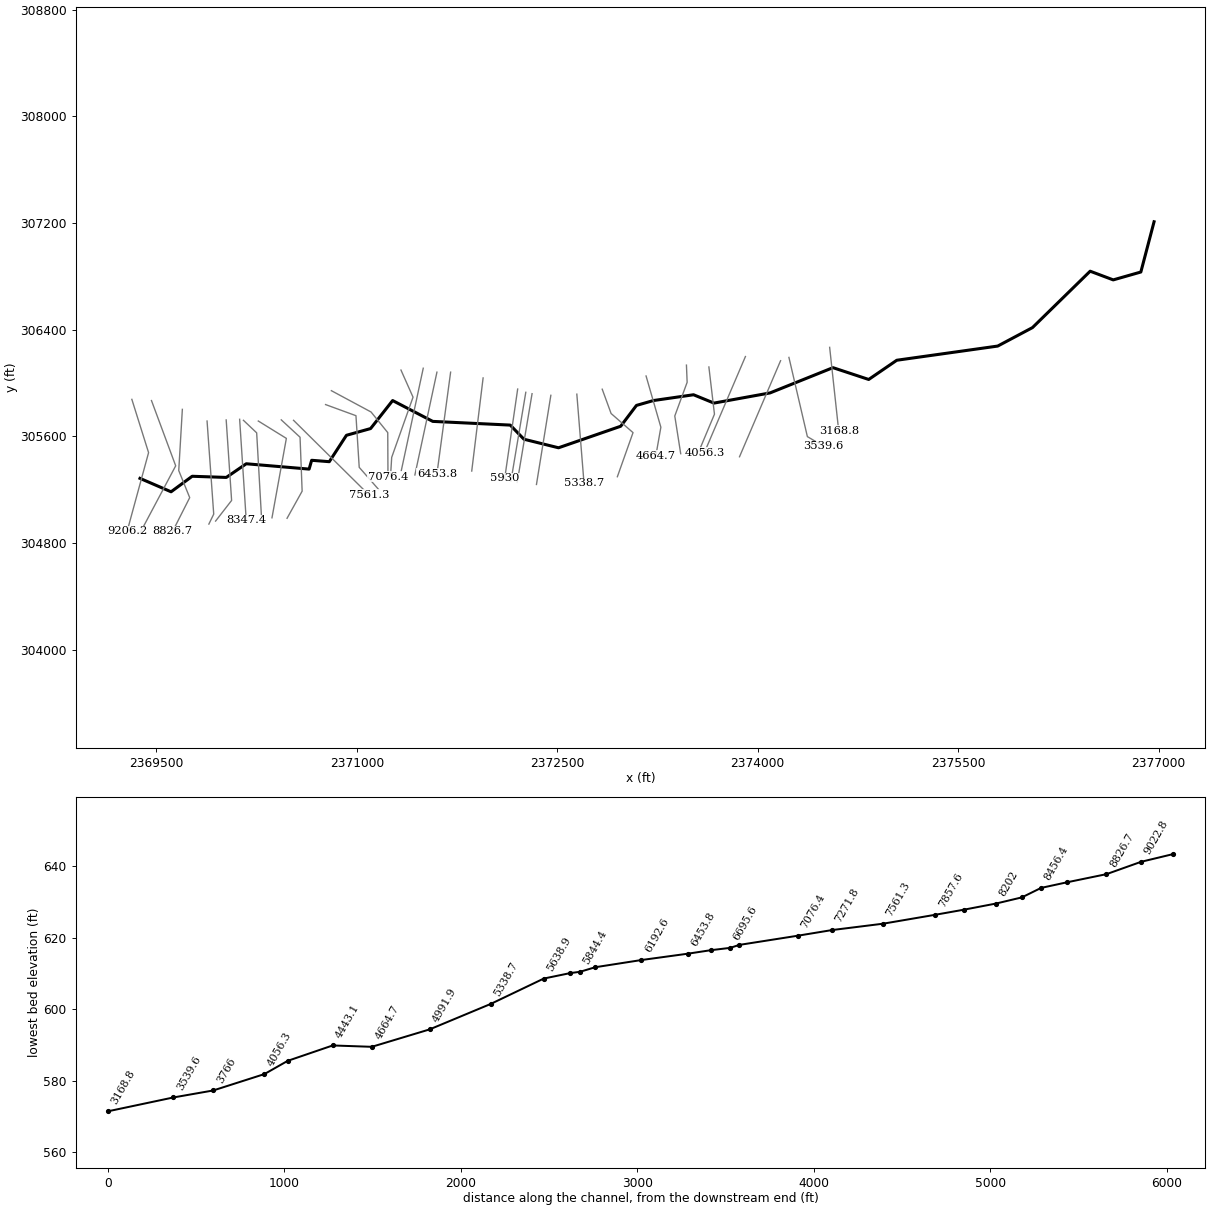
--- TORYTOWNRN.prj (project) ---

Proj Title=TORYTOWNRN
Current Plan=p01
Default Exp/Contr=0,0
English Units
Geom File=g01
Flow File=f01
Plan File=p01
BEGIN DESCRIPTION:
END DESCRIPTION:
DSS Export Rating Curves= 0
DSS Export Rating Curve Sorted= 0
DSS Export Volume Flow Curves= 0
DXF OffsetX= 0
DXF OffsetY= 0
DXF ScaleX= 0
DXF ScaleY= 0

--- TORYTOWNRN.p01 (plan) ---

Plan Title=Floodplain
Program Version=4.00
Geom File=g01
Flow File=f01
K Sum by GR=0
Std Step Tol=0.01
Critical Tol=0.01
Num of Std Step Trials=20
Max Error Tol=0.3
Flow Tol Ratio=0.001
Split Flow NTrial=30
Split Flow Tol=0.02
Split Flow Ratio=0.02
Log Output Level=0
Friction Slope Method=1
Unsteady Friction Slope Method=2
Unsteady Bridges Friction Slope Method=1
Global Log Level=0
CheckData=False
Run HTab=0
Run UNet=0
Run PostProcess=0
UNET Theta=0
UNET Theta Warmup=0
UNET ZTol=0
UNET ZSATol=0
UNET MxIter=0
UNET MaxInSteps=0
UNET DtIC=0
UNET DtMin=0
UNET MaxCRTS=0
UNET WFStab=0
UNET SFStab=0
UNET WFX=0
UNET SFX=0
UNET DSS MLevel=0
UNET DZMax Abort=0
UNET Convert EG Bridges=0
UNET Use Existing IB Tables=0
UNET Froude Limit=0
UNET Froude Power=0
Write IC File=0
Echo Input=False
Echo Output=False
Write Detailed=0

--- TORYTOWNRN.f01 (steady flow) ---

Flow Title=NFF Regression Equation
Program Version=4.10
Number of Profiles= 1
Profile Names=P100yr
River Rch & RM=TORYTOWNRN,Main            ,9206.2
528.5534
River Rch & RM=TORYTOWNRN,Main            ,9022.8
571.5399
River Rch & RM=TORYTOWNRN,Main            ,7561.3
601.4897
River Rch & RM=TORYTOWNRN,Main            ,6746.1
 667.921
River Rch & RM=TORYTOWNRN,Main            ,6584.5
720.8835
River Rch & RM=TORYTOWNRN,Main            ,4188.3
753.9126
River Rch & RM=TORYTOWNRN,Main            ,546.8
836.9973
River Rch & RM=TORYTOWNRN,Main            ,151.7
920.8924
Boundary for River Rch & Prof#=TORYTOWNRN,Main            , 1
Up Type= 0
Dn Type= 3
Dn Slope=0.00685
DSS Import GetInterval= 0
DSS Import GetPeak= 0
DSS Import FillOption= 0

--- TORYTOWNRN.g01 (geometry) ---

Geom Title=USGS 10m DEM
Program Version=5.03

River Reach=TORYTOWNRN      ,Main
Reach XY= 30
     2369377.842      305285.722     2369610.481      305185.028
     2369768.467      305301.347     2370023.676      305292.667
     2370172.981      305395.098     2370643.467      305355.167
     2370662.564      305421.139     2370794.509      305410.722
     2370922.981      305608.639     2371103.537      305658.986
     2371268.467      305869.056     2371568.814      305712.806
     2372148.676      305685.028     2372251.106      305579.125
     2372509.787      305514.889     2372975.064      305676.348
      2373093.12      305832.597     2373219.856      305869.056
     2373520.203      305912.459     2373672.981      305849.958
      2374093.12      305926.347     2374563.606      306115.584
     2374830.967      306027.042     2375041.037      306171.139
     2375796.361      306277.484     2376056.561      306415.939
     2376488.126      306838.693     2376660.836      306773.589
     2376867.425      306832.598     2376966.384      307209.334

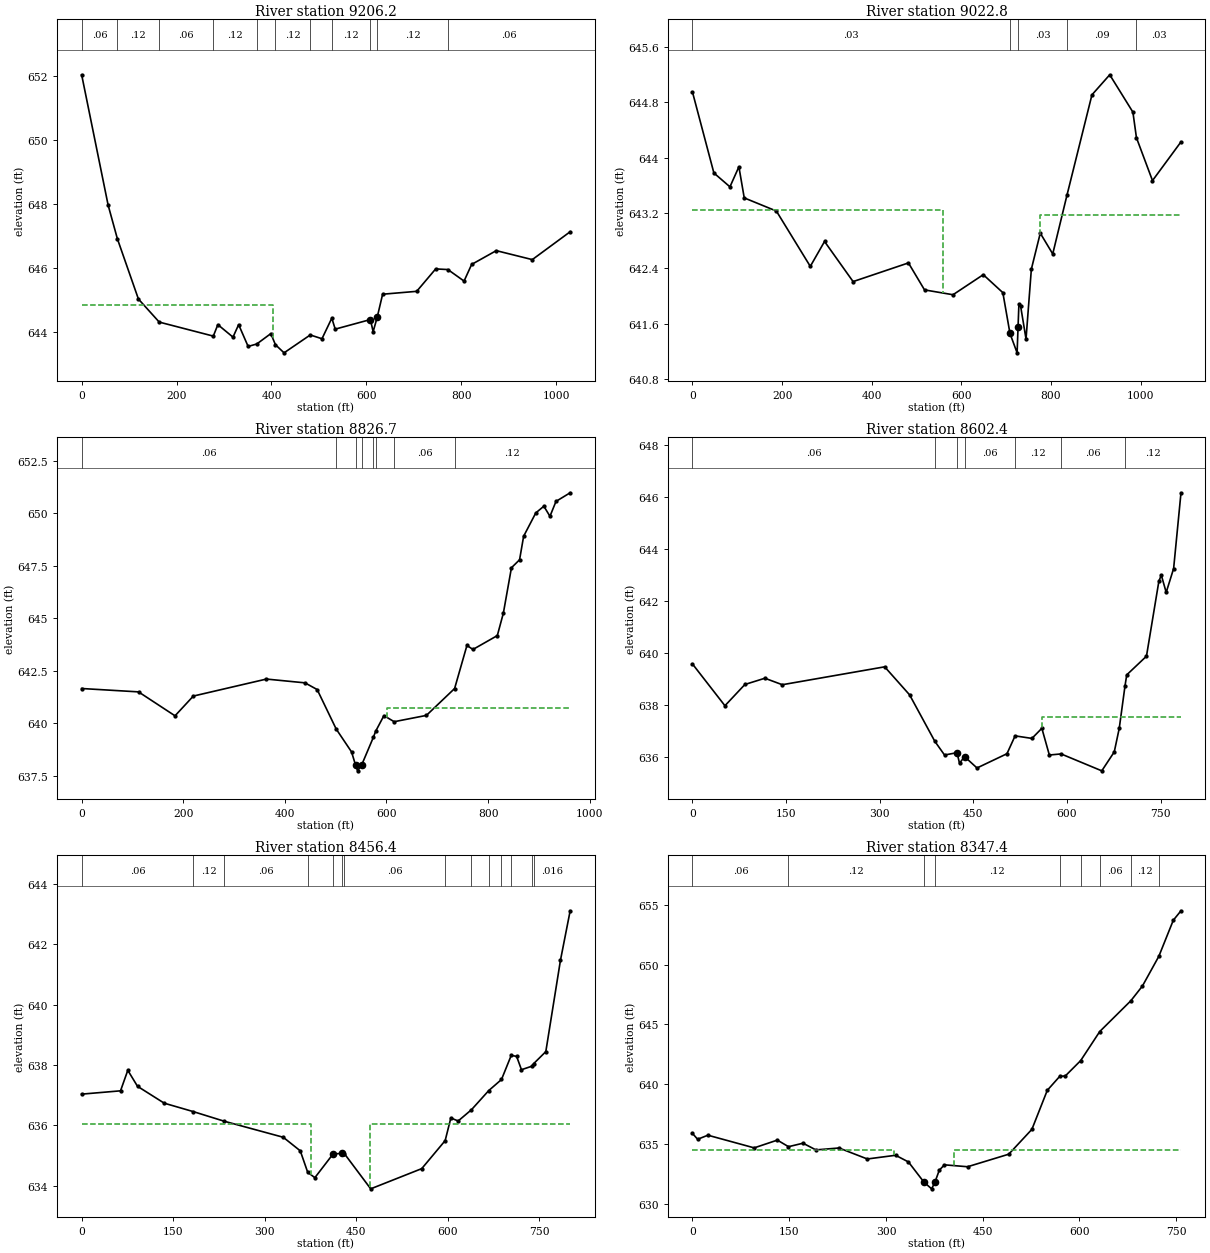
Type RM Length L Ch R = 1 ,9206.2  ,188.5,183.4,178.4
XS GIS Cut Line= 3
     2369316.999      305877.912     2369442.223      305478.545
     2369281.746      304889.089
#Sta/Elev= 30
       0  652.04    55.8  647.97   75.28646.9205   119.6  645.04  163.47644.3198
  277.41643.8821     287  644.24   318.9  643.85   330.8  644.24   350.8  643.56
  368.98643.6357   398.6  643.96  408.34643.6134   426.5  643.36  481.72643.9181
   506.4   643.8  527.13644.4426   534.3   644.1  608.48644.3991   614.2  644.02
  622.72644.4672   634.2  645.19     706  645.28     746  645.98  771.68  645.96
   805.8   645.6   821.8  646.12   873.7  646.55   949.6  646.27  1029.4  647.14
#Mann= 11 ,-1 , 0
       0     .06       0   75.28     .12       0  163.47     .06       0
  277.41     .12       0  368.98     .06       0  408.34     .12       0
  481.72     .06       0  527.13     .12       0  608.48    .045       0
  622.72     .12       0  771.68     .06       0
#XS Ineff= 2 , 0
          403.72  644.86
Permanent Ineff=
       F       F
Bank Sta=608.48,622.72
XS Rating Curve= 0 ,0
Exp/Cntr=0.3,0.1

Type RM Length L Ch R = 1 ,9022.8  ,175.8,196.1,214.7
XS GIS Cut Line= 3
       2369463.9      305868.912     2369645.124      305379.648
      2369378.83      304877.593
#Sta/Elev= 30
       0  644.95    47.8  643.78    83.6  643.58   103.6  643.87   115.5  643.42
   187.2  643.23   262.9  642.43   294.7  642.79   358.4  642.21   481.9  642.48
   517.8  642.09   581.4  642.02   648.9  642.31   692.6  642.05   708.5  641.46
   724.4  641.18   726.5  641.55   728.4  641.88   732.4  641.85   744.3  641.38
   756.2  642.39   776.1  642.91   803.9  642.61   835.7  643.46   891.4  644.91
   931.1   645.2   982.8  644.66   990.7  644.29  1026.5  643.67  1090.1  644.23
#Mann= 5 ,-1 , 0
       0     .03       0   708.5    .045       0   726.5     .03       0
   835.7     .09       0   990.7     .03       0
#XS Ineff= 2 , 0
          558.51  643.24  775.23          643.18
Permanent Ineff=
       F       F
Bank Sta=708.5,726.5
XS Rating Curve= 0 ,0
Exp/Cntr=0.3,0.1

Type RM Length L Ch R = 1 ,8826.7  ,229.9,224.3,218.7
XS GIS Cut Line= 4
     2369694.951      305803.103     2369667.909      305344.327
     2369749.941      305141.202     2369622.336      304888.597
#Sta/Elev= 30
       0  641.65   111.9  641.49   183.8  640.35   219.8  641.29   363.7   642.1
   439.6  641.92   463.6   641.6  501.07 639.719   531.3  638.63   539.2     638
   543.2  637.73   551.2  638.01   574.2 639.326  578.69639.6133     595  640.36
  615.15640.0694   678.6  640.37  734.14641.6496   758.4   643.7   770.3  643.51
   818.2  644.17   830.1  645.24     846   647.4     862  647.78     870   648.9
   893.9  650.01   909.8  650.33   921.8  649.85   933.7  650.56   961.6  650.97
#Mann= 8 ,-1 , 0
       0     .06       0  501.07     .12       0   539.2    .045       0
   551.2     .12       0   574.2     .06       0  578.69     .12       0
  615.15     .06       0  734.14     .12       0
#XS Ineff= 2 , 0
                          601.65          640.73
Permanent Ineff=
       F       F
Bank Sta=539.2,551.2
XS Rating Curve= 0 ,0
Exp/Cntr=0.3,0.1

Type RM Length L Ch R = 1 ,8602.4  ,146.5,146,145.5
XS GIS Cut Line= 3
     2369879.808      305715.494     2369929.645      305017.598
     2369893.388      304943.016
#Sta/Elev= 30
       0  639.57      52  637.96      84  638.78     116  639.02   143.9  638.77
   307.9  639.46   347.8  638.38   388.2  636.59   403.8  636.06   423.8  636.15
   427.8  635.74   435.8     636   455.8  635.56   503.8  636.11  516.84636.7982
   543.8   636.7   559.7  637.09   571.7  636.06   590.5636.1021   655.7  635.45
   675.7  636.18   683.7  637.09  692.96638.7321   695.7  639.15   727.3  639.87
   747.1  642.75     751     643   758.9  642.33   770.8  643.25   782.6  646.17
#Mann= 7 ,-1 , 0
       0     .06       0   388.2     .12       0   423.8    .045       0
   435.8     .06       0  516.84     .12       0   590.5     .06       0
  692.96     .12       0
#XS Ineff= 2 , 0
                          559.75          637.52
Permanent Ineff=
       F       F
Bank Sta=423.8,435.8
XS Rating Curve= 0 ,0
Exp/Cntr=0.3,0.1

Type RM Length L Ch R = 1 ,8456.4  ,126.7,109,108.1
XS GIS Cut Line= 3
     2370022.944      305723.667     2370063.527      305120.099
     2369943.735      304965.585
#Sta/Elev= 30
       0  637.03    63.7  637.14    75.6  637.82    91.5  637.29   135.3  636.73
  182.66636.4522  233.62636.1318   330.3   635.6   358.2  635.15  370.35634.4394
   382.1  634.26   411.7  635.04   426.7  635.07  430.53635.0545   473.6  633.89
   557.2  634.56  595.58 635.489   604.9  636.24   616.9  636.14  638.66636.5125
  667.04637.1492  687.89637.5157  703.92 638.319   712.7  638.28   720.6  637.84
  737.12 637.953   740.8 638.046   760.5  638.44   784.5  641.47   800.4  643.11
#Mann= 14 ,-1 , 0
       0     .06       0  182.66     .12       0  233.62     .06       0
  370.35     .12       0   411.7    .045       0   426.7     .12       0
  430.53     .06       0  595.58    .016       0  638.66     .12       0
  667.04    .016       0  687.89     .06       0  703.92    .016       0
  737.12     .12       0   740.8    .016       0
#XS Ineff= 2 , 0
          375.64  636.05  471.62          636.03
Permanent Ineff=
       F       F
Bank Sta=411.7,426.7
XS Rating Curve= 0 ,0
Exp/Cntr=0.3,0.1

Type RM Length L Ch R = 1 ,8347.4  ,127.1,145.4,146.3
XS GIS Cut Line= 2
     2370123.638      305728.441     2370172.902       304972.53
#Sta/Elev= 30
       0  635.88       8  635.39    23.9  635.73    95.7  634.67   131.6  635.32
  148.89634.7691   171.4  635.06   191.4   634.5   227.2  634.66   271.1  633.74
     315  634.05   334.9  633.49   358.8  631.81   370.8  631.24  375.81631.7742
   382.7   632.8   390.7  633.25   426.6  633.09   490.4  634.14   526.3  636.22
   550.2  639.49  569.48640.6575   578.1  640.69  601.93641.9754  631.55644.4114
  679.76646.9874   697.7  648.22  723.14650.7071   745.6  653.73   757.5  654.52
#Mann= 9 ,-1 , 0
       0     .06       0  148.89     .12       0   358.8    .045       0
  375.81     .12       0  569.48    .016       0  601.93     .12       0
  631.55     .06       0  679.76     .12       0  723.14     .06       0
#XS Ineff= 2 , 0
           312.9  634.52  406.19          634.52
Permanent Ineff=
       F       F
Bank Sta=358.8,375.81
XS Rating Curve= 0 ,0
Exp/Cntr=0.3,0.1

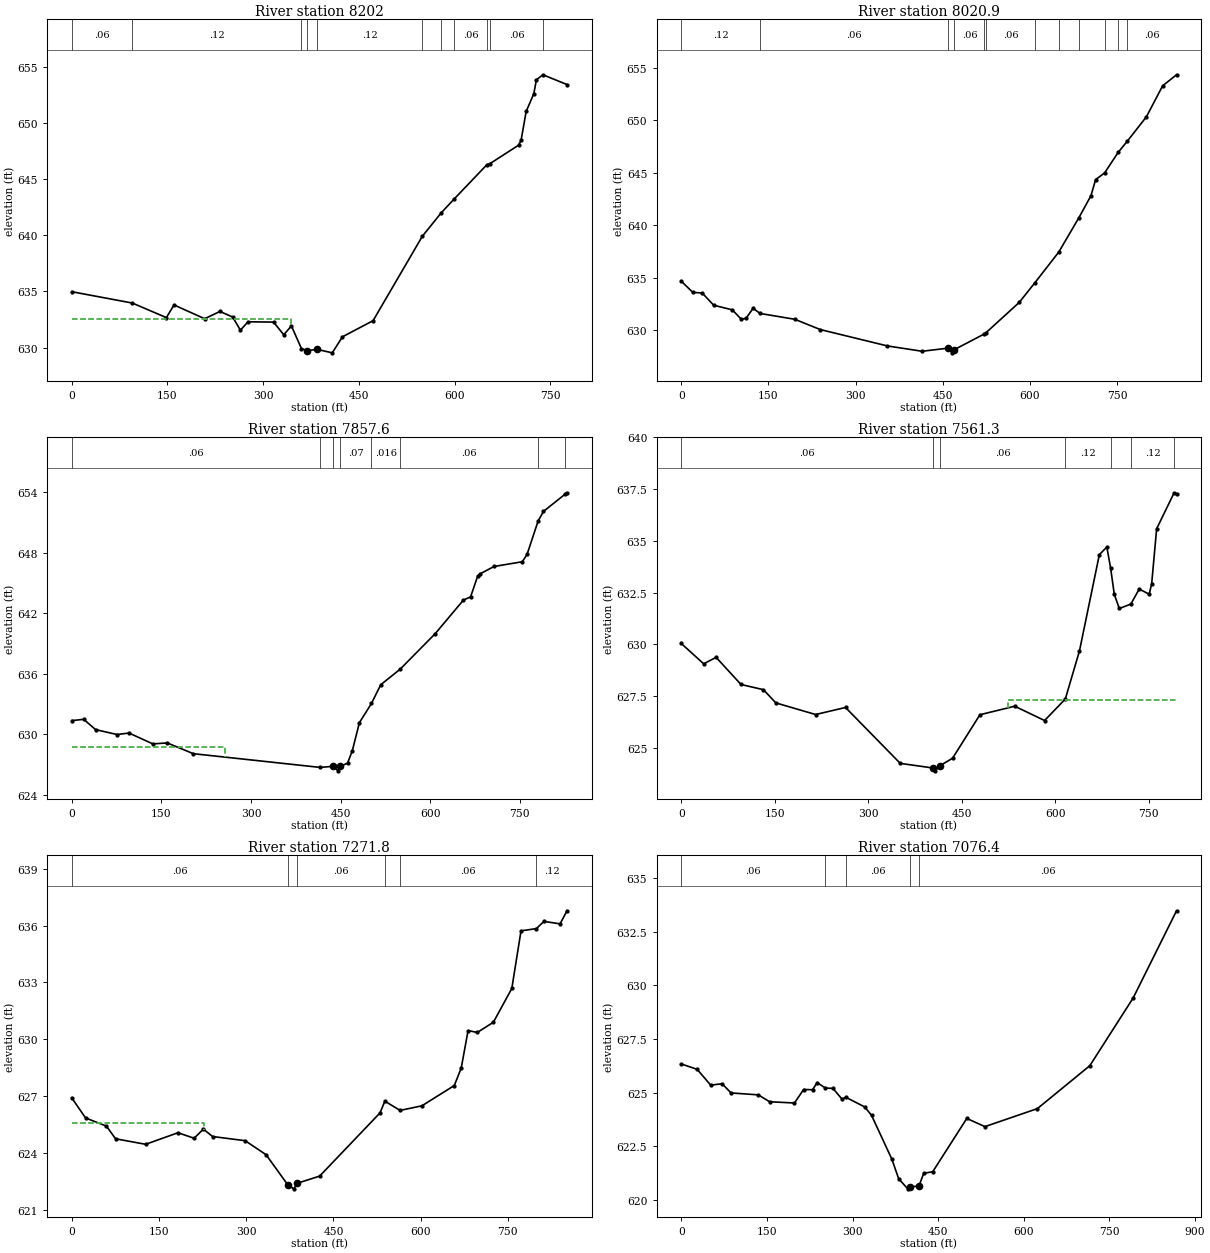
Type RM Length L Ch R = 1 ,8202    ,185.2,181.1,178.6
XS GIS Cut Line= 3
     2370152.069      305720.794     2370251.027      305627.044
     2370287.485      304988.155
#Sta/Elev= 30
       0  634.98   94.97633.9689   148.3  632.67   160.3   633.8   208.3  632.57
   232.3  633.22   252.3  632.72   264.3  631.55   276.3   632.3   316.3  632.27
   332.3  631.14   344.3  631.93     360629.9088   369.4  629.72   384.4  629.84
   408.3  629.53   424.3  630.96   472.3   632.4  549.54639.9299  579.13642.0169
  599.46643.2517  650.28646.2794   655.8  646.41   700.2  648.04   704.2  648.47
   712.2  651.05   724.2  652.63   728.2  653.87  738.43654.3198   776.2  653.45
#Mann= 11 ,-1 , 0
       0     .06       0   94.97     .12       0     360     .06       0
   369.4    .045       0   384.4     .12       0  549.54     .06       0
  579.13    .016       0  599.46     .06       0  650.28     .08       0
   655.8     .06       0  738.43     .08       0
#XS Ineff= 2 , 0
          343.45  632.55
Permanent Ineff=
       F       F
Bank Sta=369.4,384.4
XS Rating Curve= 0 ,0
Exp/Cntr=0.3,0.1

Type RM Length L Ch R = 1 ,8020.9  ,159.6,163.3,168.5
XS GIS Cut Line= 3
      2370263.18      305715.585     2370473.249      305585.377
      2370365.61      304989.891
#Sta/Elev= 30
       0  634.65    19.9  633.58    35.9  633.53    55.8  632.36    87.7  631.92
   103.6  631.01   111.6  631.12   123.6  632.07  135.63631.5739   195.3  631.02
   239.2  630.04   354.6  628.48   414.4  627.97   458.2  628.26   466.1  627.82
   470.1  628.13  521.78 629.629  524.67 629.752   581.6  632.63   608.4634.4925
  649.86 637.446  684.42640.7201     705   642.8     713  644.33  728.52644.9744
     752 646.946  767.36 647.983   800.5  650.33   828.4  653.28   852.3  654.33
#Mann= 12 ,-1 , 0
       0     .12       0  135.63     .06       0   458.2    .045       0
   470.1     .06       0  521.78     .12       0  524.67     .06       0
   608.4    .016       0  649.86     .06       0  684.42    .016       0
  728.52     .06       0     752     .12       0  767.36     .06       0
Bank Sta=458.2,470.1
XS Rating Curve= 0 ,0
Exp/Cntr=0.3,0.1

Type RM Length L Ch R = 1 ,7857.6  ,277.8,296.3,312.7
XS GIS Cut Line= 4
     2370435.055      305724.266      2370575.68      305594.058
     2370591.305      305189.544     2370478.458      304986.419
#Sta/Elev= 30
       0  631.37      20   631.5    39.9  630.48    75.9  629.99    95.8  630.14
   135.8  629.06   159.7  629.16   203.6  628.09  415.72  626.73   437.7  626.84
   445.6  626.39   449.6  626.84   461.5  627.15   469.5  628.38   481.4  631.17
  501.54633.0704   517.1  634.93  549.58636.4729   608.3     640   655.5  643.33
   667.4  643.64   679.2  645.68   683.1  645.92   706.7  646.66     754  647.13
   761.9  647.85  780.41651.1613   789.4  652.12  825.92653.8444   828.8  653.97
#Mann= 8 ,-1 , 0
       0     .06       0  415.72     .07       0   437.7    .045       0
   449.6     .07       0  501.54    .016       0  549.58     .06       0
  780.41    .016       0  825.92     .06       0
#XS Ineff= 2 , 0
          255.93   628.8
Permanent Ineff=
       F       F
Bank Sta=437.7,449.6
XS Rating Curve= 0 ,0
Exp/Cntr=0.3,0.1

Type RM Length L Ch R = 1 ,7561.3  ,306.4,289.5,272.6
XS GIS Cut Line= 2
     2370527.069      305720.794     2371091.305      305161.766
#Sta/Elev= 30
       0  630.04    35.9  629.06    55.9  629.37    95.8  628.06   131.7  627.81
   151.7  627.17   215.5  626.61   263.4  626.95   351.2  624.25   403.1  624.03
   407.1  623.89   415.1  624.14   435.1   624.5     479   626.6   534.8  627.01
   582.7  626.32  615.92627.3602   638.6  629.68   670.5  634.33   682.5   634.7
   688.6633.6745   694.5  632.41   702.5  631.73   721.1 631.945   734.4  632.67
   750.4  632.42   754.4  632.92   762.4  635.58  790.44637.3186   794.3  637.28
#Mann= 7 ,-1 , 0
       0     .06       0   403.1    .045       0   415.1     .06       0
  615.92     .12       0   688.6     .06       0   721.1     .12       0
  790.44     .06       0
#XS Ineff= 2 , 0
                          524.25           627.3
Permanent Ineff=
       F       F
Bank Sta=403.1,415.1
XS Rating Curve= 0 ,0
Exp/Cntr=0.3,0.1

Type RM Length L Ch R = 1 ,7271.8  ,181.4,195.4,209.6
XS GIS Cut Line= 4
     2370766.652      305838.849     2370994.083      305755.516
     2371018.388      305368.363     2371164.222      305201.696
#Sta/Elev= 30
       0  626.91    23.8  625.85    59.6  625.42    75.4  624.75   127.1  624.46
   182.7  625.07   210.4  624.78   226.3  625.26   242.2  624.87   298.2  624.65
   334.2  623.91   372.2  622.29   382.2  622.11   387.2   622.4   426.2  622.78
   530.2  626.12   538.4626.7355  564.61626.2479   602.1  626.49   657.8  627.56
   669.7  628.48   681.5  630.46   697.4  630.36     725   630.9   756.7  632.68
   772.5  635.72  798.92  635.84     812  636.22   839.7  636.09   851.6  636.78
#Mann= 6 ,-1 , 0
       0     .06       0   372.2    .045       0   387.2     .06       0
   538.4     .12       0  564.61     .06       0  798.92     .12       0
#XS Ineff= 2 , 0
          228.07  625.59
Permanent Ineff=
       F       F
Bank Sta=372.2,387.2
XS Rating Curve= 0 ,0
Exp/Cntr=0.3,0.1

Type RM Length L Ch R = 1 ,7076.4  ,354.5,330.3,306
XS GIS Cut Line= 4
     2370810.055      305943.016      2371106.93      305783.294
      2371231.93       305628.78     2371233.666      305297.183
#Sta/Elev= 30
       0  626.34    27.8  626.09    51.6  625.35    71.4  625.42    87.2  624.99
   134.8   624.9   154.7  624.58   198.3  624.52   214.2  625.15     230  625.14
     238  625.47  252.42625.2194   265.7   625.2   281.6   624.7  288.42624.7851
   321.2  624.34   333.2  623.95   368.9   621.9   380.8  620.99   396.7  620.52
   400.7  620.59   416.6  620.67   424.6  621.24   440.5  621.32   500.1   623.8
   531.9  623.42   623.8  624.26   715.6  626.26   791.6  629.42   867.5  633.48
#Mann= 5 ,-1 , 0
       0     .06       0  252.42    .016       0  288.42     .06       0
   400.7    .045       0   416.6     .06       0
Bank Sta=400.7,416.6
XS Rating Curve= 0 ,0
Exp/Cntr=0.3,0.1

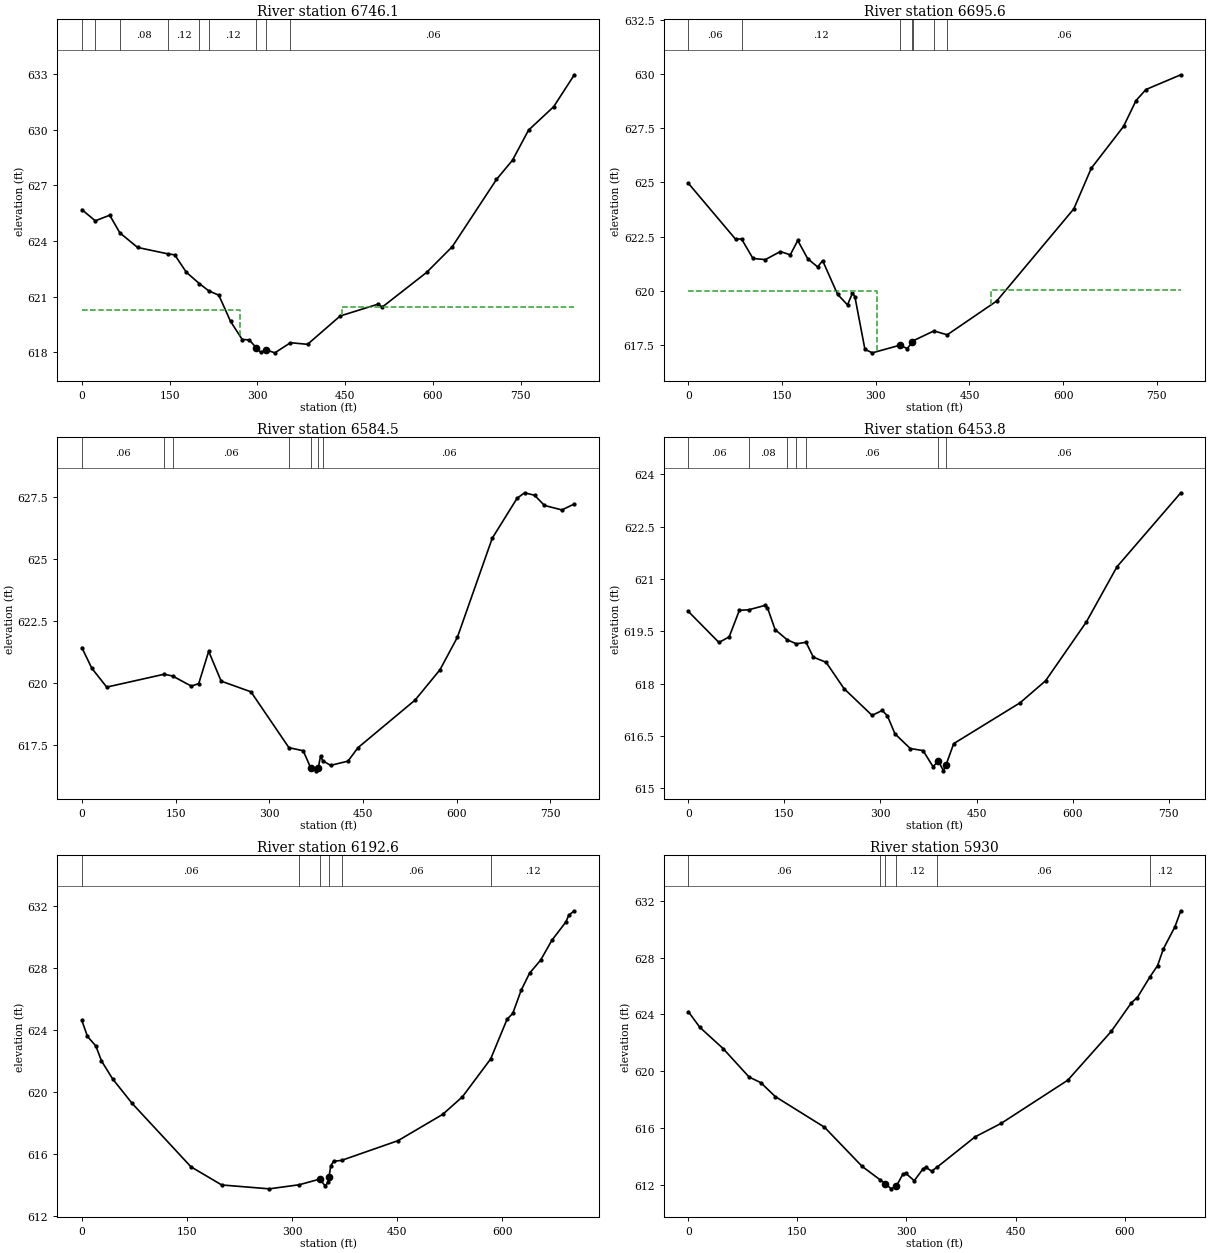
Type RM Length L Ch R = 1 ,6746.1  ,44.7,50.5,54.1
XS GIS Cut Line= 4
     2371330.888       306097.53     2371421.166      305894.405
     2371261.444      305443.016     2371252.763      305302.391
#Sta/Elev= 30
       0  625.69   23.04625.0857    47.6  625.39   65.01624.4359    95.3  623.65
  146.61623.3051   158.8  623.25   178.6  622.31  201.14 621.692  216.97621.3068
   234.2  621.07   254.2  619.66   274.2  618.68   286.1  618.66   298.1  618.24
   306.1  617.98   314.1  618.13     330  617.96   356.7 618.507   385.9  618.42
   441.7  619.95   505.6  620.58   513.6  620.43   589.4   622.3   633.3  623.69
   708.9  627.32   736.3  628.36   763.7  629.98   806.8  631.25     842  632.97
#Mann= 9 ,-1 , 0
       0     .06       0   23.04     .12       0   65.01     .08       0
  146.61     .12       0  201.14     .06       0  216.97     .12       0
   298.1    .045       0   314.1     .12       0   356.7     .06       0
#XS Ineff= 2 , 0
          270.38  620.29  444.79          620.44
Permanent Ineff=
       F       F
Bank Sta=298.1,314.1
XS Rating Curve= 0 ,0
Exp/Cntr=0.3,0.1

Type RM Length L Ch R = 1 ,6695.6  ,113.9,111.1,109.3
XS GIS Cut Line= 2
     2371497.555      306111.419     2371332.624      305340.585
#Sta/Elev= 30
       0  624.96    75.6  622.38   85.15622.3935   103.5  621.49   123.4  621.44
   147.3  621.81   163.2  621.66   175.2  622.32   191.1  621.48     207   621.1
     215  621.39   238.9  619.84   254.8  619.35   262.8   619.9   266.7  619.72
   282.7   617.3   294.6  617.14   338.4  617.49   350.4  617.34   358.3  617.62
  359.91617.6965  393.12  618.15  414.42 617.971   493.7  619.53   617.1  623.78
     645  625.65   696.7  627.58   716.6  628.77   732.5  629.28   788.3  629.96
#Mann= 7 ,-1 , 0
       0     .06       0   85.15     .12       0   338.4    .045       0
   358.3     .12       0  359.91     .06       0  393.12     .12       0
  414.42     .06       0
#XS Ineff= 2 , 0
          301.34  619.97   483.8          620.02
Permanent Ineff=
       F       F
Bank Sta=338.4,358.3
XS Rating Curve= 0 ,0
Exp/Cntr=0.3,0.1

Type RM Length L Ch R = 1 ,6584.5  ,128.9,130.7,132.3
XS GIS Cut Line= 2
     2371599.985      306081.905     2371435.055      305311.071
#Sta/Elev= 30
       0  621.44    15.9  620.61    39.8  619.85  131.94620.3687  145.36620.2943
   175.2  619.89   187.1  619.99     203  621.29     223  620.09   270.7  619.66
  331.51617.4106   354.3  617.29   366.3   616.6   374.2  616.48   378.2  616.58
   382.2  617.08  385.56616.8868   398.1   616.7     426  616.87   441.9  617.41
   533.5  619.33   573.3  620.55   601.2  621.86   656.9  625.84   696.7  627.45
   708.7  627.67   724.6  627.57   740.5  627.16   768.4  626.98   788.3  627.22
#Mann= 7 ,-1 , 0
       0     .06       0  131.94     .08       0  145.36     .06       0
  331.51     .12       0   366.3    .045       0   378.2     .12       0
  385.56     .06       0
Bank Sta=366.3,378.2
XS Rating Curve= 0 ,0
Exp/Cntr=0.3,0.1

Type RM Length L Ch R = 1 ,6453.8  ,261.4,261.2,260.7
XS GIS Cut Line= 2
     2371702.416      306081.905     2371599.985      305319.752
#Sta/Elev= 30
       0  620.07    47.8  619.18    63.8  619.34    79.7   620.1   94.61620.1175
   119.5  620.24   123.5  620.18   135.5  619.55  154.05619.2603  168.58619.1403
  183.77619.1848   195.2  618.76   215.2  618.61     243  617.86   286.9  617.09
   302.8  617.23   310.8  617.08   322.7  616.56   346.6  616.14   366.6  616.08
   382.1  615.62   390.5  615.78   398.4   615.5   402.4  615.67   414.4  616.28
     518  617.45   557.8  618.08   621.6  619.77   669.4  621.35     769  623.47
#Mann= 7 ,-1 , 0
       0     .06       0   94.61     .08       0  154.05     .12       0
  168.58     .08       0  183.77     .06       0   390.5    .045       0
   402.4     .06       0
Bank Sta=390.5,402.4
XS Rating Curve= 0 ,0
Exp/Cntr=0.3,0.1

Type RM Length L Ch R = 1 ,6192.6  ,262.9,262.6,263
XS GIS Cut Line= 2
     2371945.472      306038.502     2371860.402      305340.585
#Sta/Elev= 30
       0  624.61       8  623.58      20  622.96      28     622    43.9  620.84
    71.9  619.25   155.8  615.16   199.7  613.99   267.6  613.74  310.34614.0037
   339.8  614.37   347.6  613.91   351.5  614.18  352.74614.5069   355.5  615.24
   359.5  615.52  370.76615.5771   451.4  616.85   515.3  618.55   543.3  619.68
  583.62622.1225   607.2   624.7   615.2  625.06   627.2  626.56   639.2  627.66
   655.1  628.51   671.1  629.79   691.1  630.97   695.1   631.4   703.1  631.69
#Mann= 6 ,-1 , 0
       0     .06       0  310.34     .12       0   339.8    .045       0
  352.74     .12       0  370.76     .06       0  583.62     .12       0
Bank Sta=339.8,352.74
XS Rating Curve= 0 ,0
Exp/Cntr=0.3,0.1

Type RM Length L Ch R = 1 ,5930    ,75.6,85.6,89.4
XS GIS Cut Line= 2
     2372204.152      305955.169      2372106.93       305285.03
#Sta/Elev= 30
       0   624.2    15.9  623.09    47.8   621.6    83.6  619.59    99.6   619.2
   119.5  618.22   187.2  616.06     239   613.3  263.93612.3491   271.1  612.09
   278.8  611.72   286.1  611.92   294.8  612.73   298.7  612.83   310.7  612.29
   322.6  613.12   326.6  613.23   334.6  612.97  341.96613.2416   394.3  615.38
   430.2  616.33   521.8  619.37   581.6  622.81   609.4  624.83   617.4  625.19
  634.87626.6538   645.3  627.44   653.2  628.61   669.2  630.18   677.2   631.3
#Mann= 6 ,-1 , 0
       0     .06       0  263.93     .12       0   271.1    .045       0
   286.1     .12       0  341.96     .06       0  634.87     .12       0
Bank Sta=271.1,286.1
XS Rating Curve= 0 ,0
Exp/Cntr=0.3,0.1

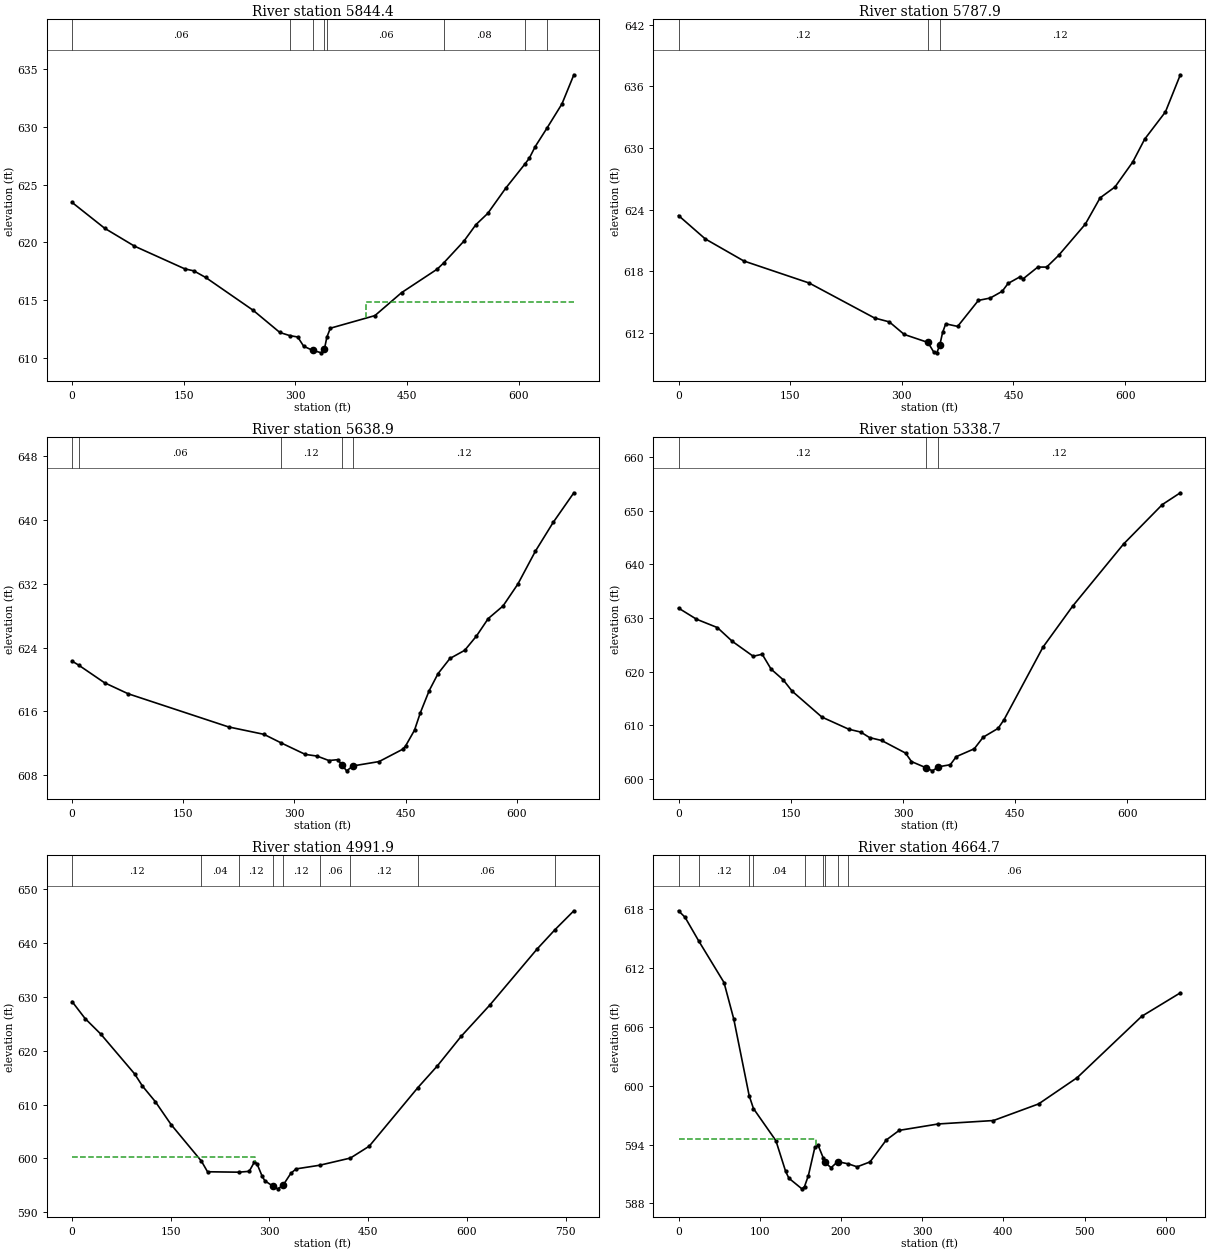
Type RM Length L Ch R = 1 ,5844.4  ,66.7,56.5,51.2
XS GIS Cut Line= 2
     2372264.916      305930.863     2372153.805      305265.933
#Sta/Elev= 30
       0  623.46    43.9  621.22    83.8  619.68   151.6  617.71   163.6  617.54
   179.5  616.97   243.3  614.13   279.2  612.21  292.56611.9396   303.2  611.82
   311.2  611.02   323.1  610.67   335.1  610.45   339.1  610.79  342.37611.8118
     347  612.58   406.9  613.67   442.8  615.66   490.6  617.69  499.59618.2442
   526.6  620.12   542.5  621.53   558.5  622.51   582.4  624.67   608.3  626.77
   614.3  627.28   622.3  628.29  638.15629.8945   658.2  631.98   674.2   634.5
#Mann= 8 ,-1 , 0
       0     .06       0  292.56     .12       0   323.1    .045       0
   339.1     .12       0  342.37     .06       0  499.59     .08       0
   608.3     .06       0  638.15     .12       0
#XS Ineff= 2 , 0
                          395.15          614.86
Permanent Ineff=
       F       F
Bank Sta=323.1,339.1
XS Rating Curve= 0 ,0
Exp/Cntr=0.3,0.1

Type RM Length L Ch R = 1 ,5787.9  ,148.6,149,148.9
XS GIS Cut Line= 2
     2372311.791      305920.446      2372200.68      305255.516
#Sta/Elev= 30
       0  623.43    35.9  621.16    87.8  619.01   175.5  616.87   263.3  613.47
   283.2  613.09   303.2  611.87   335.1  611.09   343.1  610.13     347  610.08
     351  610.83   354.8  612.06     359   612.9     375  612.65   402.9  615.18
   418.8  615.41   434.8  616.06   442.8  616.83   458.7  617.47   462.7  617.26
   482.7  618.42   494.6  618.42   510.6  619.55   546.5  622.59   566.4  625.15
   586.4  626.21   610.3  628.64   626.3  630.86   654.2  633.51   674.2  637.12
#Mann= 3 ,-1 , 0
       0     .12       0   335.1    .045       0     351     .12       0
Bank Sta=335.1,351
XS Rating Curve= 0 ,0
Exp/Cntr=0.3,0.1

Type RM Length L Ch R = 1 ,5638.9  ,293.3,300.1,307
XS GIS Cut Line= 2
     2372452.416      305908.294     2372344.777      305239.891
#Sta/Elev= 30
       0   622.3    8.72621.8098    43.8  619.59    75.7  618.21   211.1  614.06
   258.9  613.13  281.66 612.077   314.6  610.62   330.5  610.41   346.5  609.85
   358.4  609.96   364.2  609.29   370.4  608.56   379.2  609.18   414.2  609.72
     446  611.26     450  611.68     462  613.65   469.9  615.84   481.9  618.62
   493.8  620.74   509.8  622.63   529.7  623.65   545.6  625.44   561.5  627.63
   581.4   629.2   601.4  631.94   625.2  636.08   649.1  639.67     677  643.38
#Mann= 5 ,-1 , 0
       0     .12       0    8.72     .06       0  281.66     .12       0
   364.2    .045       0   379.2     .12       0
Bank Sta=364.2,379.2
XS Rating Curve= 0 ,0
Exp/Cntr=0.3,0.1

Type RM Length L Ch R = 1 ,5338.7  ,328.6,346.8,365
XS GIS Cut Line= 2
      2372646.86      305916.974      2372700.68      305248.571
#Sta/Elev= 30
       0  631.82      24  629.75    51.9  628.19    71.8  625.63    99.8  622.84
   111.8  623.22   123.7  620.44   139.7  618.48   151.7  616.35   191.6   611.5
   227.5  609.24   243.5  608.71   255.4  607.67   271.4  607.14   303.4  604.79
   311.3  603.21   331.3  602.02   339.3  601.48   347.3  602.23   363.2  602.62
   371.2  604.13   395.2  605.59   407.1  607.75   427.1   609.4   435.1  611.04
     487  624.53   526.9  632.22   594.7  643.76   646.6  651.13   670.6  653.32
#Mann= 3 ,-1 , 0
       0     .12       0   331.3    .045       0   347.3     .12       0
Bank Sta=331.3,347.3
XS Rating Curve= 0 ,0
Exp/Cntr=0.3,0.1

Type RM Length L Ch R = 1 ,4991.9  ,337.4,327.3,309
XS GIS Cut Line= 4
     2372836.878      305954.144     2372903.284      305771.853
     2373067.347      305628.623     2372950.159      305297.894
#Sta/Elev= 30
       0  629.11    19.8  625.96    43.6  623.08      95   615.7   106.9  613.44
   126.7  610.51   150.5  606.28  196.52599.5076   205.9  597.52  253.72597.4416
   269.2   597.6   277.2  599.34   281.1     599     289  596.67     293  595.85
   304.9  594.87   312.8  594.35   320.7  595.02   332.6  597.24   340.5  598.05
  376.46598.7333   423.1600.0662   451.7  602.27  525.46613.1181   555.3  617.18
   591.2  622.63   635.1  628.48   706.8  638.86  734.07642.4578   762.7  645.96
#Mann= 9 ,-1 , 0
       0     .12       0  196.52     .04       0  253.72     .12       0
   304.9    .045       0   320.7     .12       0  376.46     .06       0
   423.1     .12       0  525.46     .06       0  734.07     .12       0
#XS Ineff= 2 , 0
           277.4  600.24
Permanent Ineff=
       F       F
Bank Sta=304.9,320.7
XS Rating Curve= 0 ,0
Exp/Cntr=0.3,0.1

Type RM Length L Ch R = 1 ,4664.7  ,236.1,221.5,206.8
XS GIS Cut Line= 3
     2373165.003      306053.103      2373275.68      305668.988
     2373237.919      305454.144
#Sta/Elev= 30
       0  617.78       8  617.12   25.04614.6844      56  610.48      68  606.77
   86.97 598.971   92.25597.6588   119.9  594.39   131.9  591.26   135.9  590.57
   151.9  589.49  155.14589.7249   159.9  590.84   167.9  593.72   171.9  593.92
  178.39592.5964   179.9   592.2   187.9  591.64   195.9  592.26  209.17592.0273
   219.9  591.73   235.8  592.23   255.8  594.46   271.8  595.44   319.8  596.09
   387.8  596.44   443.4  598.13     491  600.81   570.3  607.04   617.9  609.43
#Mann= 9 ,-1 , 0
       0     .06       0   25.04     .12       0   86.97     .06       0
   92.25     .04       0  155.14     .12       0  178.39     .06       0
   179.9    .045       0   195.9     .12       0  209.17     .06       0
#XS Ineff= 2 , 0
          169.04  594.58
Permanent Ineff=
       F       F
Bank Sta=179.9,195.9
XS Rating Curve= 0 ,0
Exp/Cntr=0.3,0.1

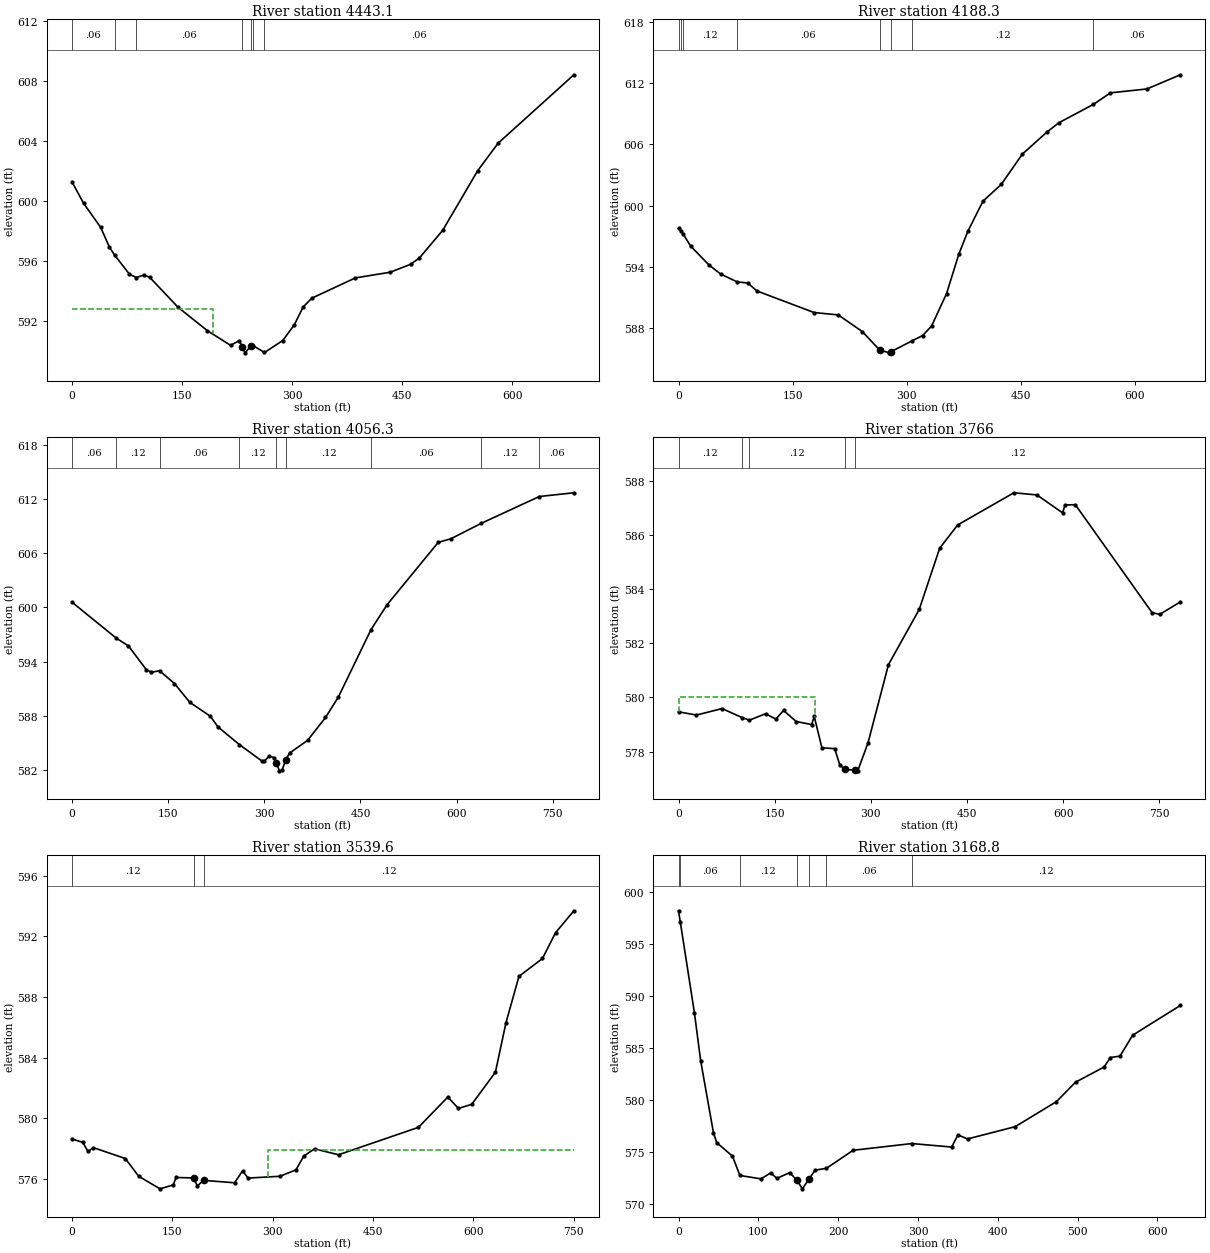
Type RM Length L Ch R = 1 ,4443.1  ,244.3,254.9,265.4
XS GIS Cut Line= 4
     2373467.086        306134.7     2373472.294      306005.794
     2373379.847      305753.189     2373424.117      305470.637
#Sta/Elev= 30
       0  601.25    15.6  599.84    39.1  598.22    50.8  596.92   57.92596.3823
    78.2  595.11   87.49594.8876    97.7  595.05   105.6  594.91   144.8  592.89
   184.4  591.35     216  590.37   227.9  590.68   231.9  590.29   235.8  589.87
   243.7  590.32  247.01590.3448  262.27589.8932   287.2  590.69   303.1  591.75
   314.9  592.92   326.8  593.51   386.1  594.86   433.8  595.24   461.6  595.77
   473.5  596.19   505.2  598.03   552.9     602   580.7  603.83     684  608.39
#Mann= 7 ,-1 , 0
       0     .06       0   57.92     .12       0   87.49     .06       0
   231.9    .045       0   243.7     .06       0  247.01     .12       0
  262.27     .06       0
#XS Ineff= 2 , 0
          191.43  592.81
Permanent Ineff=
       F       F
Bank Sta=231.9,243.7
XS Rating Curve= 0 ,0
Exp/Cntr=0.3,0.1

Type RM Length L Ch R = 1 ,4188.3  ,145.6,132,118
XS GIS Cut Line= 3
     2373635.055      306120.811     2373676.722      305766.644
     2373559.534      305486.696
#Sta/Elev= 30
       0  597.77    3.22597.5043    6.11597.2128    15.8  596.05    39.6  594.21
    55.5  593.29   76.92592.5335    91.1  592.41     103  591.64   178.3  589.52
     210  589.29   241.7  587.66   264.5  585.85   277.4  585.57   279.5  585.68
  307.68586.7674     321  587.26   332.8  588.19   352.6  591.38   368.6  595.22
   380.6  597.49   400.5  600.44   424.5  602.08   452.4  605.06   484.4   607.2
   500.4  608.13  545.52609.9171   568.2  611.06   616.2  611.44   660.1  612.83
#Mann= 8 ,-1 , 0
       0     .12       0    3.22     .06       0    6.11     .12       0
   76.92     .06       0   264.5    .045       0   279.5     .06       0
  307.68     .12       0  545.52     .06       0
Bank Sta=264.5,279.5
XS Rating Curve= 0 ,0
Exp/Cntr=0.3,0.1

Type RM Length L Ch R = 1 ,4056.3  ,289.9,290.2,290.3
XS GIS Cut Line= 2
     2373908.492      306198.936     2373601.201      305478.884
#Sta/Elev= 30
       0  600.58   69.23596.5803    87.9  595.74   115.8   593.1   123.8  592.81
  136.51592.9769   159.8  591.56   183.7  589.47   215.7  587.93   227.7  586.74
  261.01 584.786   295.6  582.99   299.6  582.93   307.6   583.5   315.6  583.32
   318.5  582.77   323.5  581.87   327.5  581.91   333.5  583.12   339.5  583.85
   367.5  585.25   395.4  587.79   415.4  590.05  466.48597.5527   491.3  600.29
   571.2  607.22   591.2  607.63  637.88609.3212  728.98612.3151   782.9  612.73
#Mann= 9 ,-1 , 0
       0     .06       0   69.23     .12       0  136.51     .06       0
  261.01     .12       0   318.5    .045       0   333.5     .12       0
  466.48     .06       0  637.88     .12       0  728.98     .06       0
Bank Sta=318.5,333.5
XS Rating Curve= 0 ,0
Exp/Cntr=0.3,0.1

Type RM Length L Ch R = 1 ,3766    ,211.6,226.5,241.3
XS GIS Cut Line= 2
     2374171.513      306167.686     2373864.222      305447.634
#Sta/Elev= 30
       0  579.47      28  579.35    67.9  579.59    98.9  579.26  110.62579.1611
   135.8   579.4   151.8   579.2   163.8  579.52   183.7  579.11   207.7     579
   211.7   579.3   223.7  578.14   243.6  578.11   251.6  577.51   259.6  577.34
   275.6  577.32   279.6  577.29   295.6  578.32   327.5  581.21   375.5  583.25
   407.4  585.51   435.4  586.37   523.2  587.56   559.2  587.48   599.1  586.82
   603.1  587.11   619.1  587.12   738.9  583.13   750.9  583.07   782.9  583.53
#Mann= 5 ,-1 , 0
       0     .12       0    98.9     .06       0  110.62     .12       0
   259.6    .045       0   275.6     .12       0
#XS Ineff= 2 , 0
          212.18  580.03
Permanent Ineff=
       F       F
Bank Sta=259.6,275.6
XS Rating Curve= 0 ,0
Exp/Cntr=0.3,0.1

Type RM Length L Ch R = 1 ,3539.6  ,320.5,370.7,357.6
XS GIS Cut Line= 3
     2374234.013      306192.426     2374372.034      305598.676
     2374493.128      305527.061
#Sta/Elev= 30
       0  578.62    15.9   578.4    23.9   577.8    31.9  578.05    79.7  577.33
    99.6  576.16   131.5  575.33   151.4  575.59   155.4  576.08   181.6  576.05
   187.3  575.52   196.6  575.89     243  575.73     255  576.52     263  576.04
   310.8  576.16   334.7  576.58   346.6   577.5   362.6  577.97   398.4  577.58
   517.9  579.39   561.8  581.39   577.7  580.64   597.6  580.91     633  583.03
   648.7  586.28   668.2  589.36   703.4  590.54   722.9  592.24   750.3  593.69
#Mann= 3 ,-1 , 0
       0     .12       0   181.6    .045       0   196.6     .12       0
#XS Ineff= 2 , 0
                          292.26          577.87
Permanent Ineff=
       F       F
Bank Sta=181.6,196.6
XS Rating Curve= 0 ,0
Exp/Cntr=0.3,0.1

Type RM Length L Ch R = 1 ,3168.8  ,356.2,366.7,376.2
XS GIS Cut Line= 2
     2374538.701      306267.946     2374606.409      305642.946
#Sta/Elev= 30
       0  598.21    2.17597.1522    19.9  588.39    27.8  583.75    43.8  576.84
    47.8  575.91    67.6   574.6   76.89572.7462   103.4  572.42   115.4  572.99
   123.3  572.47   139.3  573.02   148.2   572.3   155.2  571.46   163.2  572.37
   171.1  573.26  185.23573.4324   218.8  575.17  292.35575.8179   342.2  575.48
   350.1  576.65   362.1  576.26   421.8  577.44   473.5  579.85   497.4  581.72
   533.2  583.18   541.1  584.09   553.1  584.23     569  586.24   628.7   589.1
#Mann= 7 ,-1 , 0
       0    .016       0    2.17     .06       0   76.89     .12       0
   148.2    .045       0   163.2     .12       0  185.23     .06       0
  292.35     .12       0
Bank Sta=148.2,163.2
XS Rating Curve= 0 ,0
Exp/Cntr=0.3,0.1