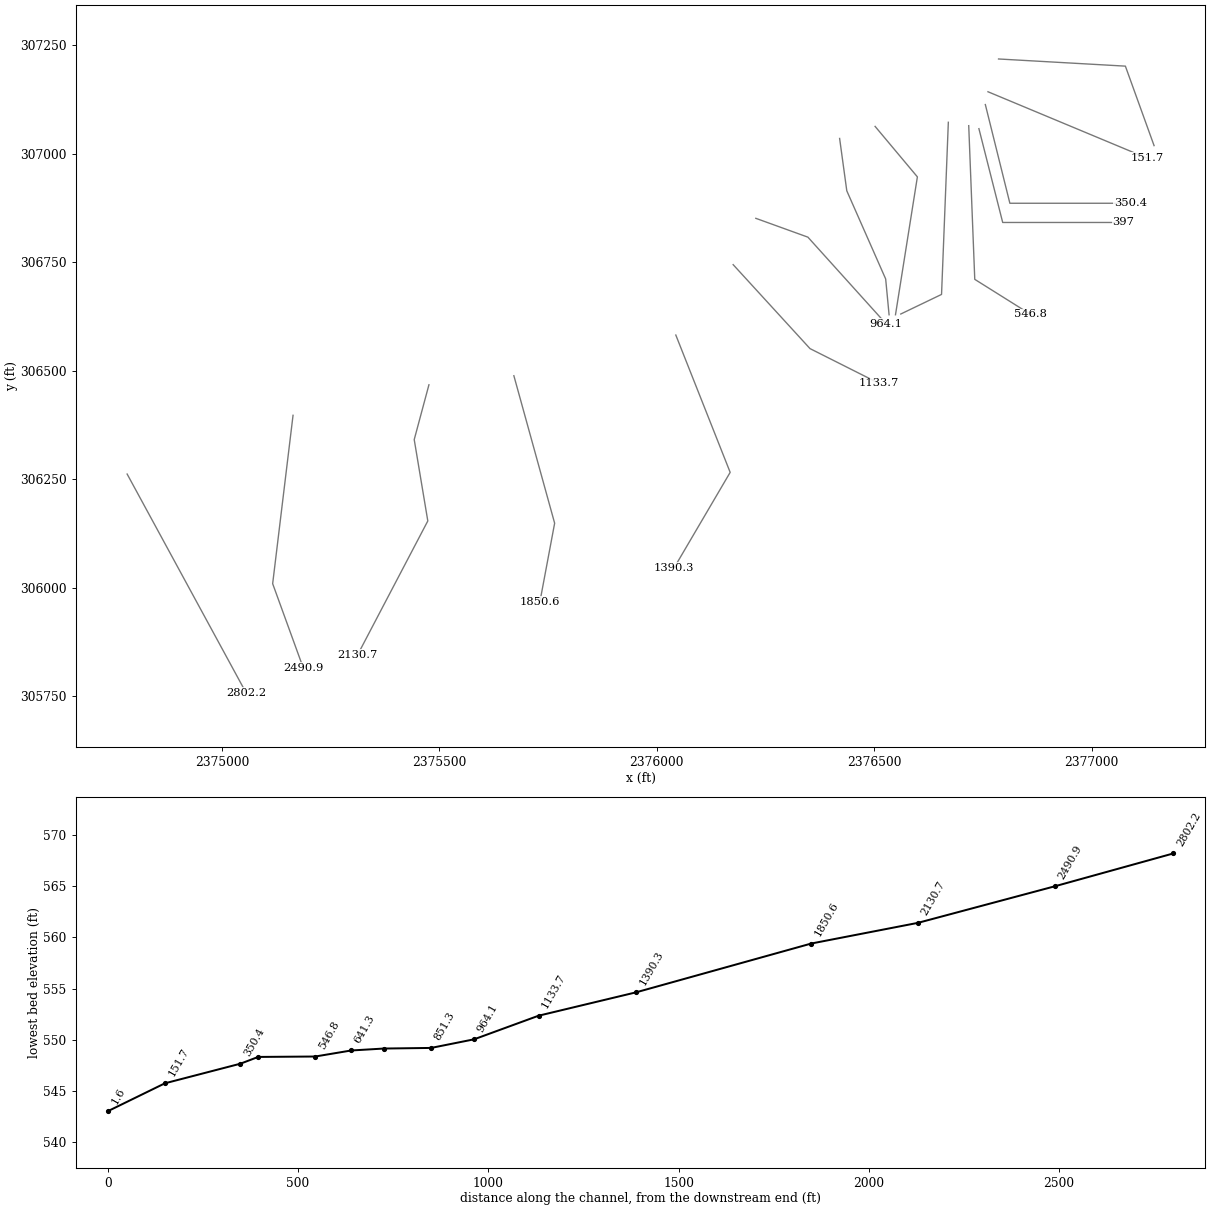
HEC-RAS study TORYTOWNRN.prj: TORYTOWNRN

--- TORYTOWNRN.g01 (geometry) --- (continued)

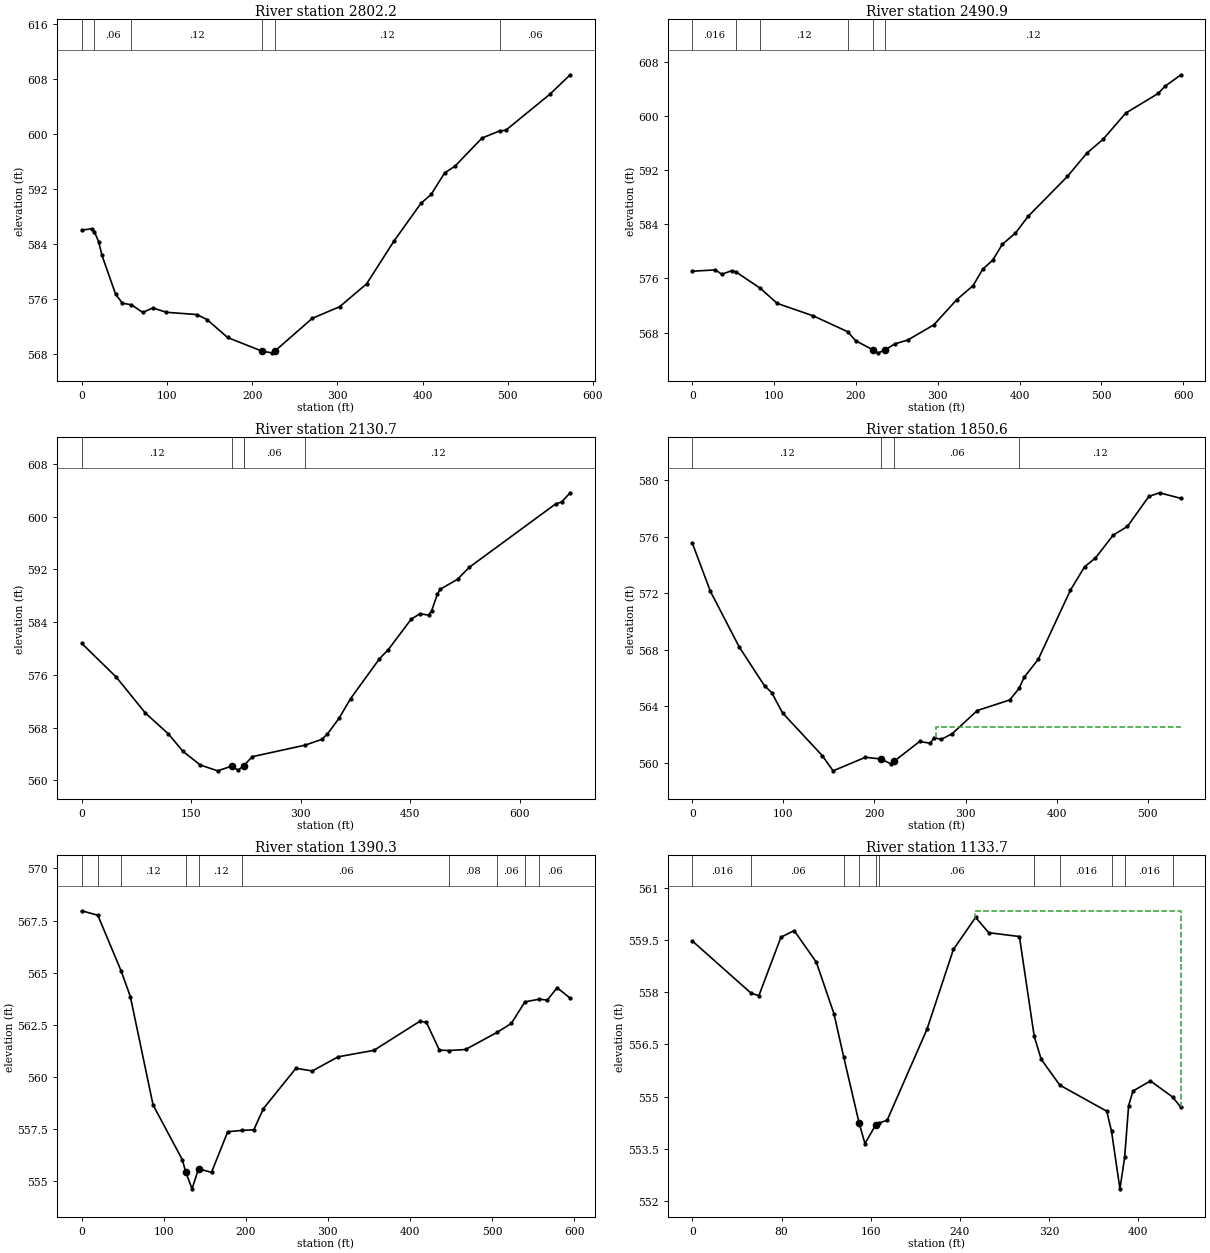
Type RM Length L Ch R = 1 ,2802.2  ,312.4,311.2,293.5
XS GIS Cut Line= 2
      2374782.19      306261.436     2375055.628       305757.53
#Sta/Elev= 30
       0  586.04    11.9  586.25   15.01585.7913    19.9  584.37    23.9  582.36
    39.8  576.75    47.8  575.43   58.37   575.2    71.7  574.09    83.6  574.74
    99.5  574.11   135.4  573.78   147.3  573.04   171.2  570.45   211.5  568.47
     223  568.22   226.5  568.45   270.7  573.24   302.6  574.91   334.4  578.24
   366.3  584.42   398.1  589.93   410.1  591.23     426  594.36     438  595.32
   469.8  599.42  490.39600.4504   497.7  600.55   549.4  605.78   573.3  608.61
#Mann= 6 ,-1 , 0
       0    .016       0   15.01     .06       0   58.37     .12       0
   211.5    .045       0   226.5     .12       0  490.39     .06       0
Bank Sta=211.5,226.5
XS Rating Curve= 0 ,0
Exp/Cntr=0.3,0.1

Type RM Length L Ch R = 1 ,2490.9  ,351.8,360.2,368.5
XS GIS Cut Line= 3
     2375163.701      306396.853     2375116.826      306008.832
     2375187.138      305814.821
#Sta/Elev= 30
       0  577.06    27.9  577.25    35.9  576.61    47.9  577.13    53.1576.9585
   82.77574.5566   103.7   572.3   147.6  570.47   189.7568.1313   199.4  566.81
   220.6  565.45   227.3  565.01   235.6  565.44   247.3  566.33   263.2   566.9
   295.1  569.14     323  572.85     343  574.92     355  577.38   366.9  578.66
   378.9  581.04   394.8  582.68   410.7   585.2   458.3  591.04   482.1  594.48
     502  596.53   529.7   600.4   569.4   603.3   577.4  604.33   597.2  606.05
#Mann= 6 ,-1 , 0
       0    .016       0    53.1     .06       0   82.77     .12       0
   189.7     .06       0   220.6    .045       0   235.6     .12       0
Bank Sta=220.6,235.6
XS Rating Curve= 0 ,0
Exp/Cntr=0.3,0.1

Type RM Length L Ch R = 1 ,2130.7  ,277.5,280.1,283.3
XS GIS Cut Line= 4
     2375476.201      306467.165     2375442.347      306340.863
     2375473.597      306153.363     2375312.138      305844.769
#Sta/Elev= 30
       0  580.78    47.6  575.63    87.2  570.21   118.9  567.02   138.7  564.39
   162.4  562.32   186.2  561.43     206  562.16   213.9  561.53   221.8  562.17
     222562.2037   233.7  563.58  305.85565.3225   328.8   566.2   336.7  567.03
   352.5   569.4   368.3  572.39   407.9  578.44   419.8   579.8   451.4  584.45
   463.3  585.26   475.2  585.06   479.2  585.68   487.1   588.2     491  588.98
   514.8  590.49   530.6  592.29   649.3  601.94   657.2  602.21   669.1  603.62
#Mann= 5 ,-1 , 0
       0     .12       0     206    .045       0   221.8     .12       0
     222     .06       0  305.85     .12       0
Bank Sta=206,221.8
XS Rating Curve= 0 ,0
Exp/Cntr=0.3,0.1

Type RM Length L Ch R = 1 ,1850.6  ,436.4,460.2,455.8
XS GIS Cut Line= 3
     2375671.513      306487.998     2375765.263      306148.155
     2375731.409      305967.165
#Sta/Elev= 30
       0  575.51    19.8  572.11    51.5  568.17    79.2  565.43    87.1  564.95
      99  563.51   142.6  560.49   154.5  559.41   190.1  560.37   206.8  560.25
   217.9  559.91   221.8   560.1   249.6  561.49   261.4  561.36   265.4  561.76
   273.3  561.64   285.2  562.03   312.9  563.68   348.6  564.43  358.78565.2441
   364.3  566.02     380  567.32   415.2   572.2   430.9  573.87   442.6  574.47
   462.2   576.1   477.9  576.72   501.4  578.84   513.2   579.1   536.7   578.7
#Mann= 4 ,-1 , 0
       0     .12       0   206.8    .045       0   221.8     .06       0
  358.78     .12       0
#XS Ineff= 2 , 0
                          267.49          562.52
Permanent Ineff=
       F       F
Bank Sta=206.8,221.8
XS Rating Curve= 0 ,0
Exp/Cntr=0.3,0.1

Type RM Length L Ch R = 1 ,1390.3  ,248.1,256.6,265.4
XS GIS Cut Line= 3
     2376043.909      306581.748     2376168.909      306265.342
     2376040.003       306045.29
#Sta/Elev= 30
       0  567.97   19.67567.7562   47.99 565.096    59.3  563.86      87  558.66
   122.6  556.04   126.6  555.47   134.5  554.64   142.4   555.6   158.2  555.43
     178  557.38  195.91557.4411   209.7  557.47   221.5  558.49   261.1  560.42
   280.9  560.29   312.5  560.97   356.1  561.28   411.9  562.67   419.9  562.63
   435.8  561.29  447.97561.2704   467.7  561.32  506.11562.1404   523.5  562.57
  539.99563.6029  557.43563.7308   567.3  563.69   579.3  564.28   595.2  563.78
#Mann= 10 ,-1 , 0
       0     .08       0   19.67     .06       0   47.99     .12       0
   126.6    .045       0   142.4     .12       0  195.91     .06       0
  447.97     .08       0  506.11     .06       0  539.99     .08       0
  557.43     .06       0
Bank Sta=126.6,142.4
XS Rating Curve= 0 ,0
Exp/Cntr=0.3,0.1

Type RM Length L Ch R = 1 ,1133.7  ,169.6,169.7,169.3
XS GIS Cut Line= 3
     2376175.803      306743.948     2376352.503      306550.498
     2376510.055      306471.071
#Sta/Elev= 30
       0  559.47   52.54557.9742    59.6   557.9    79.4  559.58    91.3  559.77
   111.2  558.86     127  557.38  135.82 556.126   149.5  554.25   154.8  553.65
   164.5  554.19     167554.2355   174.7  554.32   210.4  556.93   234.2  559.23
   254.1  560.15   265.9  559.71   293.4   559.6  306.71556.7299     313  556.07
   329.7555.3292   371.8  554.58  376.07554.0037   383.6  552.35  387.84553.2521
   391.4  554.74   395.3  555.16     411  555.45  430.83  554.99   438.4  554.69
#Mann= 11 ,-1 , 0
       0    .016       0   52.54     .06       0  135.82     .12       0
   149.5    .045       0   164.5     .12       0     167     .06       0
  306.71     .08       0   329.7    .016       0  376.07     .08       0
  387.84    .016       0  430.83     .12       0
#XS Ineff= 2 , 0
                          253.35          560.34
Permanent Ineff=
       F       F
Bank Sta=149.5,164.5
XS Rating Curve= 0 ,0
Exp/Cntr=0.3,0.1

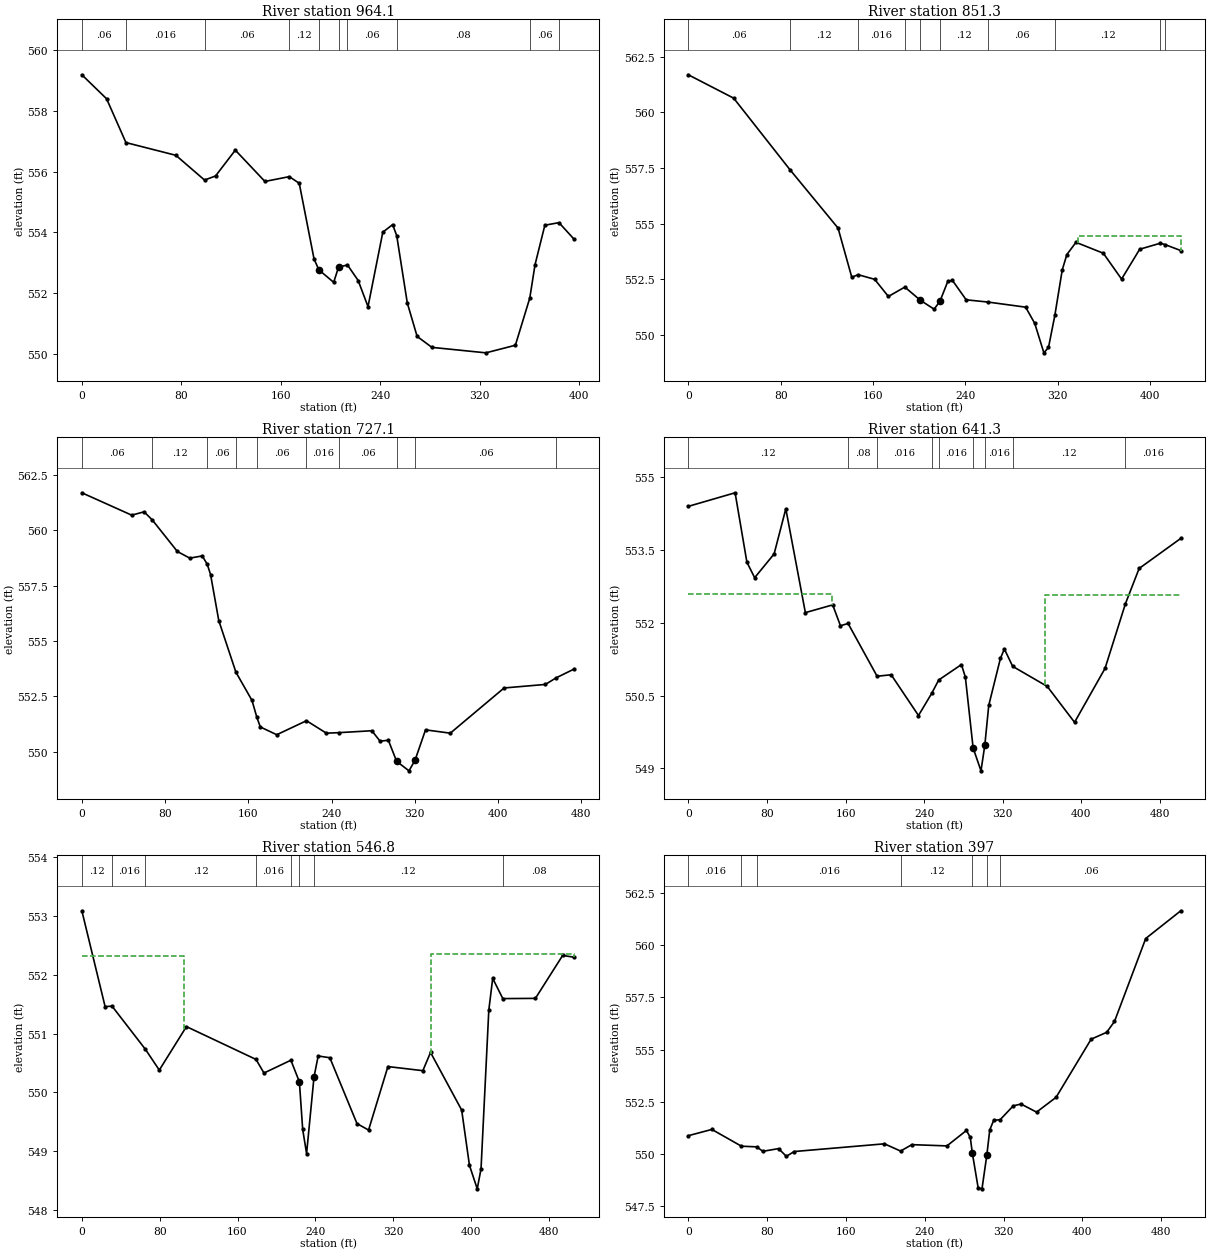
Type RM Length L Ch R = 1 ,964.1   ,120.2,112.8,105.2
XS GIS Cut Line= 3
     2376227.886      306850.719     2376347.675      306807.314
     2376527.365      306607.664
#Sta/Elev= 30
       0  559.19    19.9   558.4   35.44556.9588    75.6  556.54   98.66555.7251
   107.5  555.86   123.4  556.71   147.2  555.68   166.8 555.838   174.8  555.62
   186.7  553.13   190.6  552.77   202.5  552.36   206.4  552.86  213.59552.9315
   222.2  552.42   230.1  551.56     242  554.01   249.9  554.26  253.17553.8995
   261.7  551.68   269.6  550.58   281.5  550.22   324.9  550.04   348.6  550.29
  360.18551.8424   364.4  552.94   372.3  554.24  383.67554.3239     396  553.77
#Mann= 10 ,-1 , 0
       0     .06       0   35.44    .016       0   98.66     .06       0
   166.8     .12       0   190.6    .045       0   206.4     .12       0
  213.59     .06       0  253.17     .08       0  360.18     .06       0
  383.67     .08       0
Bank Sta=190.6,206.4
XS Rating Curve= 0 ,0
Exp/Cntr=0.3,0.1

Type RM Length L Ch R = 1 ,851.3   ,136.1,124.2,111.6
XS GIS Cut Line= 4
     2376420.595      307034.747     2376437.088      306914.087
     2376526.497      306710.962      2376534.31      306628.497
#Sta/Elev= 30
       0  561.68    39.3  560.63   87.98557.4239   129.7   554.8   141.6  552.59
  147.04552.7079   161.4   552.5   173.3  551.73  187.54552.1515     201  551.56
   212.9  551.16  217.92551.5091   224.8  552.41   228.8  552.45   240.7  551.58
  259.56551.4794   292.2  551.25   300.1  550.52     308   549.2     312  549.44
  317.49550.8766   323.9  552.92   327.9  553.61   335.8  554.16   359.5  553.67
   375.3  552.51     391  553.85  408.83554.1194  413.06554.0568   426.6  553.79
#Mann= 10 ,-1 , 0
       0     .06       0   87.98     .12       0  147.04    .016       0
  187.54     .12       0     201    .045       0  217.92     .12       0
  259.56     .06       0  317.49     .12       0  408.83     .06       0
  413.06    .016       0
#XS Ineff= 2 , 0
                          337.46          554.46
Permanent Ineff=
       F       F
Bank Sta=201,217.92
XS Rating Curve= 0 ,0
Exp/Cntr=0.3,0.1

Type RM Length L Ch R = 1 ,727.1   ,89.4,85.8,88.4
XS GIS Cut Line= 3
     2376502.192      307062.525     2376599.414      306946.205
     2376549.067      306628.497
#Sta/Elev= 30
       0  561.69    47.9  560.68    59.8  560.83   67.68560.4648    91.8  559.04
   103.7  558.74   115.7  558.84   120.5 558.464   123.7     558   131.6  555.92
  148.06553.5925   163.5  552.32   168.1551.5705   171.5  551.12   187.3  550.77
   215.9 551.402     235  550.84  247.07550.8636   278.7  550.95   286.6  550.48
   294.6  550.52   302.5  549.57   314.4  549.14  320.24549.6222   330.3  550.99
   354.1  550.84   405.8  552.88   445.5  553.04  455.74553.3351   473.3  553.74
#Mann= 10 ,-1 , 0
       0     .06       0   67.68     .12       0   120.5     .06       0
  148.06     .12       0   168.1     .06       0   215.9    .016       0
  247.07     .06       0   302.5    .045       0  320.24     .06       0
  455.74    .016       0
Bank Sta=302.5,320.24
XS Rating Curve= 0 ,0
Exp/Cntr=0.3,0.1

Type RM Length L Ch R = 1 ,641.3   ,84.9,94.5,96.9
XS GIS Cut Line= 3
     2376670.595      307072.073      2376654.97      306675.372
      2376561.22      306630.233
#Sta/Elev= 30
       0   554.4    47.6  554.68    59.6  553.25    67.5  552.93    87.3  553.42
    99.2  554.35   119.1  552.21   146.9  552.37   154.8  551.94  162.57551.9865
  192.09550.8991   206.4  550.93   234.2  550.09  247.61 550.545  254.79550.8224
   277.9  551.14   281.9  550.88   289.8  549.42   297.8  548.95   301.7  549.48
   305.7   550.3   317.6  551.27   321.6  551.46  330.03551.1033   365.2  550.69
     393  549.95     424  551.06  444.74552.3925   458.7  553.12   501.1  553.74
#Mann= 9 ,-1 , 0
       0     .12       0  162.57     .08       0  192.09    .016       0
  247.61     .06       0  254.79    .016       0   289.8    .045       0
   301.7    .016       0  330.03     .12       0  444.74    .016       0
#XS Ineff= 2 , 0
          146.13  552.59  362.85          552.58
Permanent Ineff=
       F       F
Bank Sta=289.8,301.7
XS Rating Curve= 0 ,0
Exp/Cntr=0.3,0.1

Type RM Length L Ch R = 1 ,546.8   ,66.3,149.8,187.2
XS GIS Cut Line= 3
      2376717.47      307064.261     2376731.358      306710.094
     2376859.831      306629.365
#Sta/Elev= 30
       0  553.09    23.9  551.46   31.04551.4678   65.35550.7329    79.6  550.38
   107.5  551.12  179.01550.5614   187.2  550.33  214.85550.5477   223.6  550.18
     227  549.37     231  548.96   238.6  550.26   242.9  550.62   254.9  550.59
   282.8  549.47   294.7  549.36   314.6  550.44   350.5  550.37   358.4  550.68
   390.4   549.7   398.4  548.76   406.4  548.36   410.3   548.7   418.3   551.4
   422.3  551.94  432.71551.5961   466.2   551.6   494.2  552.33   506.2   552.3
#Mann= 8 ,-1 , 0
       0     .12       0   31.04    .016       0   65.35     .12       0
  179.01    .016       0  214.85     .12       0   223.6    .045       0
   238.6     .12       0  432.71     .08       0
#XS Ineff= 2 , 0
          104.64  552.32  359.13          552.36
Permanent Ineff=
       F       F
Bank Sta=223.6,238.6
XS Rating Curve= 0 ,0
Exp/Cntr=0.3,0.1

Type RM Length L Ch R = 1 ,397     ,88.9,46.6,51.9
XS GIS Cut Line= 3
     2376740.907      307057.316     2376795.595      306841.171
     2377072.504      306841.171
#Sta/Elev= 30
       0  550.87    23.9  551.17   53.94550.3651   69.52550.3345    75.6  550.12
    91.6  550.25    99.5  549.88   107.5  550.11   199.1  550.48  215.45550.1321
   226.9  550.44   262.5  550.38   282.3  551.12   286.2  550.79   288.3550.0353
   294.2  548.37   298.1  548.32     303549.9339     306  551.15     310  551.61
  316.49551.6342   329.8   552.3   337.7  552.39   353.5     552   373.3  552.71
   408.9   555.5   424.7  555.83   432.6  556.35   464.3  560.33   499.9  561.66
#Mann= 7 ,-1 , 0
       0    .016       0   53.94     .12       0   69.52    .016       0
  215.45     .12       0   288.3    .045       0     303     .12       0
  316.49     .06       0
Bank Sta=288.3,303
XS Rating Curve= 0 ,0
Exp/Cntr=0.3,0.1

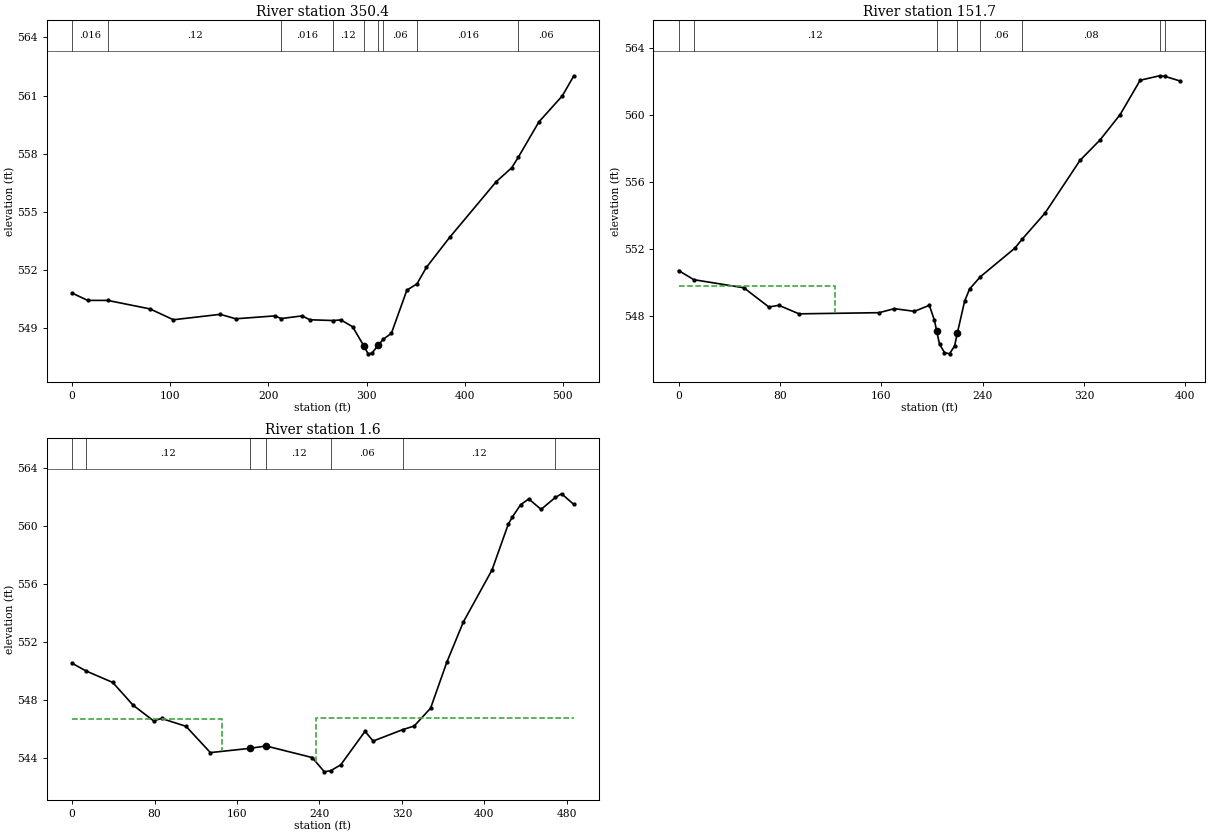
Type RM Length L Ch R = 1 ,350.4   ,208.8,198.6,184.3
XS GIS Cut Line= 3
     2376755.664      307112.872     2376812.088      306885.441
     2377088.997      306885.441
#Sta/Elev= 30
       0   550.8    15.9  550.42   36.32550.4193    79.4  549.98   103.3  549.42
   150.9   549.7   166.8  549.47   206.5  549.62  213.03549.4821   234.3  549.62
   242.2  549.42  265.83549.3804   273.9  549.41   285.8  549.06     297  548.09
   301.6  547.66   305.5  547.69     312  548.12   317.2  548.42   325.3  548.72
   341.1  550.95  351.37 551.274   360.9  552.12   384.6  553.67   432.1  556.55
   447.9  557.27  454.55 557.811   475.6  559.64   499.4  560.98   511.2  562.02
#Mann= 9 ,-1 , 0
       0    .016       0   36.32     .12       0  213.03    .016       0
  265.83     .12       0     297    .045       0     312     .12       0
   317.2     .06       0  351.37    .016       0  454.55     .06       0
Bank Sta=297,312
XS Rating Curve= 0 ,0
Exp/Cntr=0.3,0.1

Type RM Length L Ch R = 1 ,151.7   ,142.4,150.1,157.8
XS GIS Cut Line= 2
      2376761.74      307142.386     2377127.192      306989.608
#Sta/Elev= 30
       0  550.72   12.11550.1705    51.5  549.69    71.3  548.54    79.2  548.64
    95.1  548.13   158.4   548.2   170.3  548.44   186.2  548.28     198  548.64
     202  547.74  203.73547.1259     206  546.32   209.9  545.82   213.9  545.74
   217.9  546.21  220.01546.9567   225.8  548.88   229.7  549.61  238.17550.3425
   265.4  552.05  271.11552.5798   289.2  554.14   316.9   557.3   332.7  558.52
   348.6  560.04   364.4  562.09  379.71562.3571  384.06562.3215   396.1  562.04
#Mann= 8 ,-1 , 0
       0    .016       0   12.11     .12       0  203.73    .045       0
  220.01     .12       0  238.17     .06       0  271.11     .08       0
  379.71     .12       0  384.06     .08       0
#XS Ineff= 2 , 0
          123.43  549.78
Permanent Ineff=
       F       F
Bank Sta=203.73,220.01
XS Rating Curve= 0 ,0
Exp/Cntr=0.3,0.1

Type RM Length L Ch R = 1 ,1.6     ,0.4,1.6,2.9
XS GIS Cut Line= 3
     2376786.046      307217.907     2377077.713      307201.414
     2377143.685      307018.254
#Sta/Elev= 30
       0  550.52   13.51549.9886    39.5  549.19    59.2  547.62      79  546.54
    86.8   546.7   110.5  546.16   134.2  544.34   173.1  544.64   188.1   544.8
   232.9     544   244.8  543.01  251.12543.0984   260.6  543.49   284.2  545.81
   292.1  545.14  320.73545.9266   331.9  546.18   347.8  547.41   363.6   550.6
   379.5  553.36   407.4  556.97   423.2  560.14   427.2  560.64   435.2  561.49
   443.1  561.88     455  561.16  468.88561.9891   474.9  562.24   486.8   561.5
#Mann= 7 ,-1 , 0
       0     .08       0   13.51     .12       0   173.1    .045       0
   188.1     .12       0  251.12     .06       0  320.73     .12       0
  468.88     .08       0
#XS Ineff= 2 , 0
          145.51  546.67  236.33          546.71
Permanent Ineff=
       F       F
Bank Sta=173.1,188.1
XS Rating Curve= 0 ,0
Exp/Cntr=0.3,0.1
LCMann Table=0

Chan Stop Cuts=-1
Use User Specified Reach Order=0
Composite Channel Slope=5